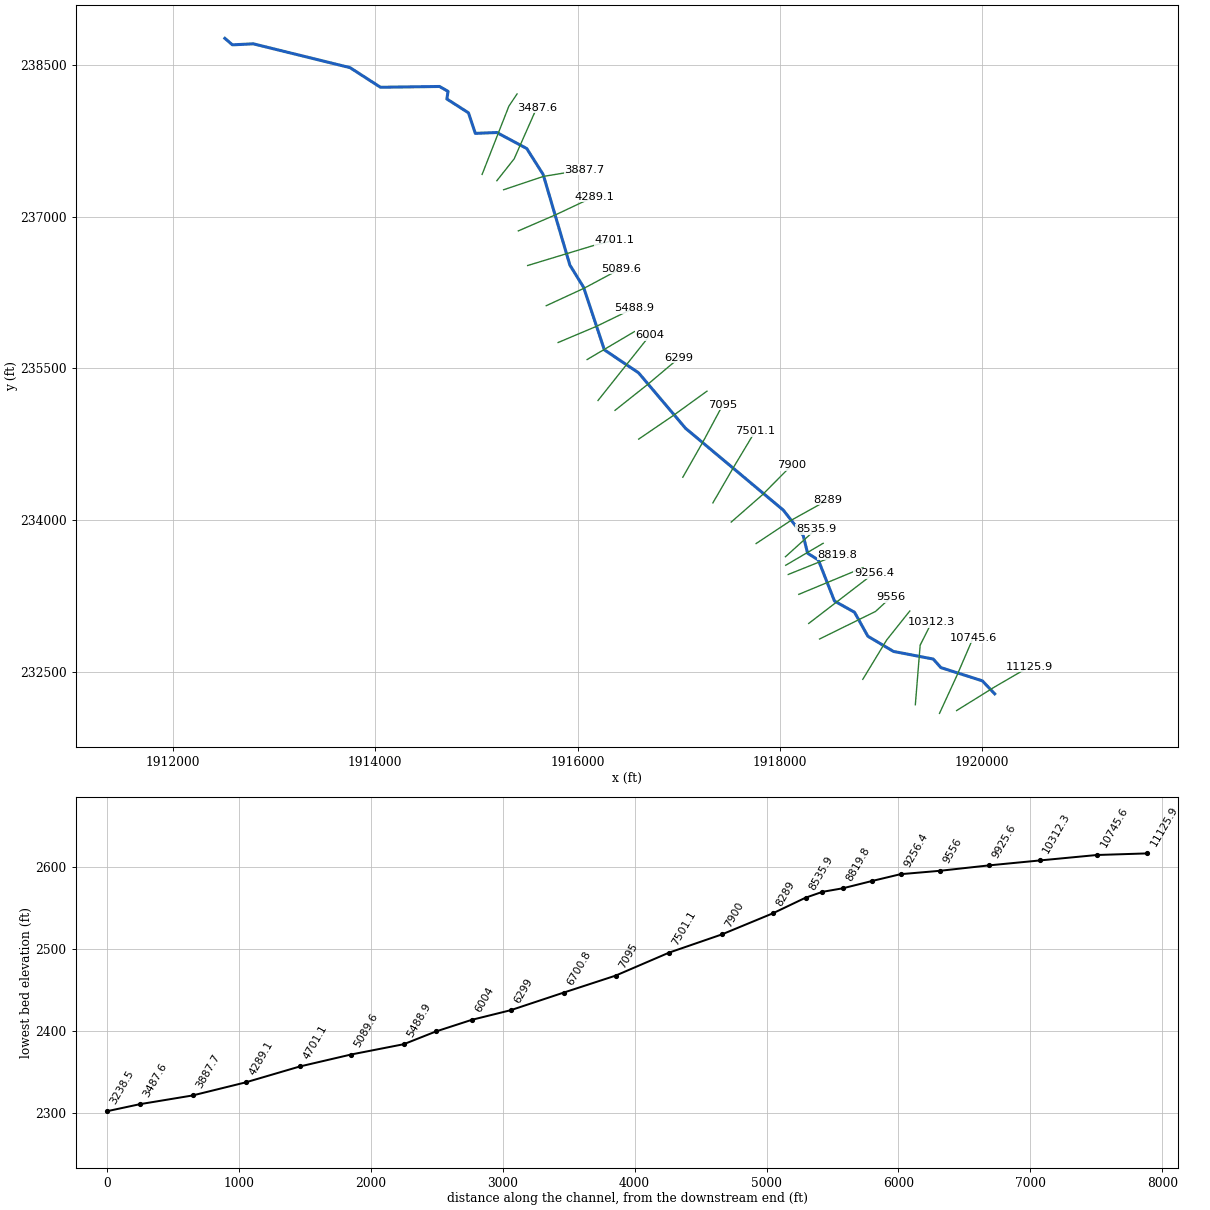
--- LrlCrk.prj (project) ---

Proj Title=LrlCrk
Current Plan=p01
Default Exp/Contr=0,0
English Units
Geom File=g01
Flow File=f01
Plan File=p01
BEGIN DESCRIPTION:
END DESCRIPTION:
DSS Export Rating Curves= 0
DSS Export Rating Curve Sorted= 0
DSS Export Volume Flow Curves= 0
DXF OffsetX= 0
DXF OffsetY= 0
DXF ScaleX= 0
DXF ScaleY= 0

--- LrlCrk.p01 (plan) ---

Plan Title=Floodplain
Program Version=4.00
Geom File=g01
Flow File=f01
K Sum by GR=0
Std Step Tol=0.01
Critical Tol=0.01
Num of Std Step Trials=20
Max Error Tol=0.3
Flow Tol Ratio=0.001
Split Flow NTrial=30
Split Flow Tol=0.02
Split Flow Ratio=0.02
Log Output Level=0
Friction Slope Method=1
Unsteady Friction Slope Method=2
Unsteady Bridges Friction Slope Method=1
Global Log Level=0
CheckData=False
Run HTab=0
Run UNet=0
Run PostProcess=0
UNET Theta=0
UNET Theta Warmup=0
UNET ZTol=0
UNET ZSATol=0
UNET MxIter=0
UNET MaxInSteps=0
UNET DtIC=0
UNET DtMin=0
UNET MaxCRTS=0
UNET WFStab=0
UNET SFStab=0
UNET WFX=0
UNET SFX=0
UNET DSS MLevel=0
UNET DZMax Abort=0
UNET Convert EG Bridges=0
UNET Use Existing IB Tables=0
UNET Froude Limit=0
UNET Froude Power=0
Write IC File=0
Echo Input=False
Echo Output=False
Write Detailed=0

--- LrlCrk.f01 (steady flow) ---

Flow Title=NFF Regression Equation
Program Version=4.10
Number of Profiles= 1
Profile Names=P100yr
River Rch & RM=LrlCrk,Main            ,11125.9
496.3172
River Rch & RM=LrlCrk,Main            ,9556
535.6406
River Rch & RM=LrlCrk,Main            ,7501.1
594.3168
River Rch & RM=LrlCrk,Main            ,4701.1
639.8363
River Rch & RM=LrlCrk,Main            ,3887.7
 709.515
River Rch & RM=LrlCrk,Main            ,3238.5
726.6639
Boundary for River Rch & Prof#=LrlCrk,Main            , 1
Up Type= 0
Dn Type= 1
Dn Known WS=2314.5
DSS Import GetInterval= 0
DSS Import GetPeak= 0
DSS Import FillOption= 0

--- LrlCrk.g01 (geometry) ---

Geom Title=USGS 3m DEM
Program Version=4.10

River Reach=LrlCrk          ,Main
Reach XY= 30
     1920125.239      232279.993     1920002.585      232408.893
     1919593.093      232539.404     1919517.027      232624.167
      1919124.77      232699.323     1918871.082      232849.518
     1918738.651      233087.096     1918540.643      233197.708
     1918381.018      233604.058     1918274.829      233670.851
     1918231.572      233845.048     1918035.381      234096.254
     1917067.714      234906.207     1916602.896      235454.999
     1916265.134      235681.715     1916059.774      236300.266
     1915924.243      236519.824     1915660.013       237415.74
      1915497.56       237672.68     1915201.695      237830.916
     1914989.036      237822.405     1914921.307      238025.606
     1914707.691       238162.38     1914719.416      238237.928
     1914634.751      238286.124     1914051.204      238278.323
     1913750.318      238472.411     1912793.131      238708.052
     1912587.139      238697.782     1912512.587      238762.226

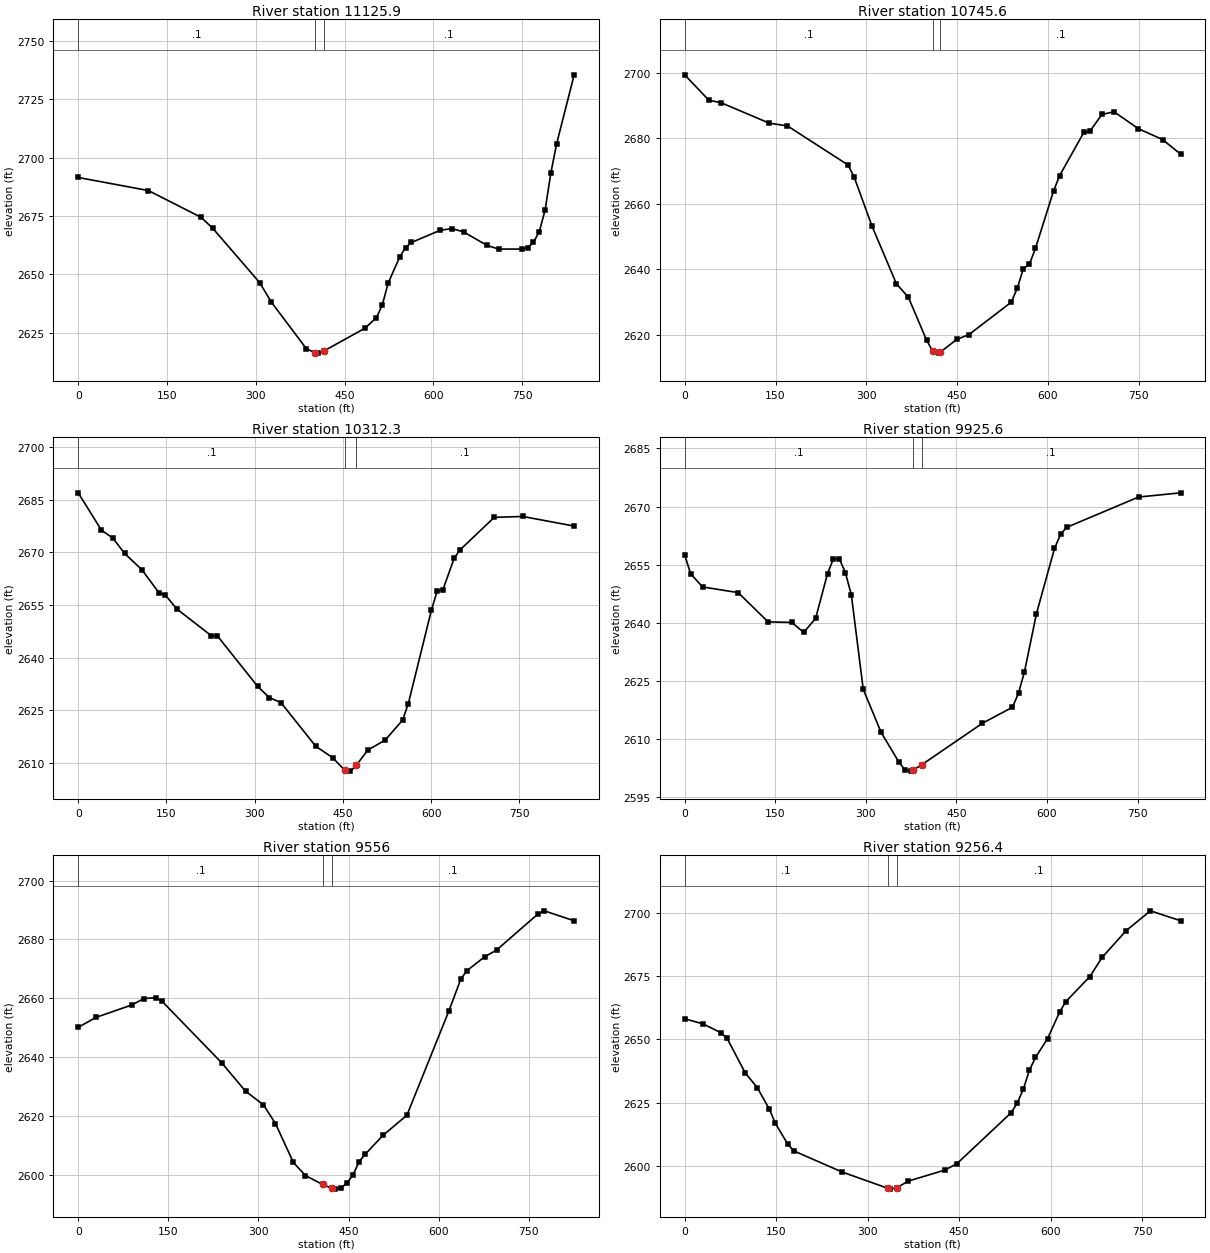
Type RM Length L Ch R = 1 ,11125.9 ,366,380.2,394.5
XS GIS Cut Line= 3
     1919748.616      232114.798     1920118.013      232344.629
      1920466.12      232547.165
#Sta/Elev= 30
       0 2691.56   118.6 2685.96   207.6 2674.48   227.4 2669.76   306.5 2646.53
   326.3 2638.15   385.6 2618.16     400  2616.5   405.4 2616.31     415 2617.23
   484.2 2626.95   503.8 2631.49   513.6 2636.87   523.5 2646.22   543.1 2657.52
   552.9 2661.53   562.8 2663.71   611.9 2668.97   631.5 2669.66   651.2 2668.23
   690.4 2662.47   710.1  2660.9   749.4 2660.88   759.2 2661.56     769 2663.76
   778.9 2668.33   788.7 2677.56   798.5  2693.6   808.3 2706.11   837.8 2735.54
#Mann= 3 , 0 , 0
       0      .1       0     400    .045       0     415      .1       0
Bank Sta=400,415
XS Rating Curve= 0 ,0
Exp/Cntr=0.3,0.1

Type RM Length L Ch R = 1 ,10745.6 ,425.6,433.2,440.8
XS GIS Cut Line= 3
     1919579.297      232087.025     1919750.356      232459.056
      1919912.23      232835.369
#Sta/Elev= 30
       0 2699.34      40 2691.57    59.9 2690.84   139.8 2684.58   169.8 2683.74
   269.6 2671.84   279.6 2668.28   309.6 2653.05   349.6 2635.59   369.5  2631.4
   399.5 2618.34   409.5 2614.99   419.5 2614.37   422.2 2614.65   449.4 2618.57
   469.4 2620.02   539.4 2629.92   549.4 2634.23   559.4 2640.18   569.3 2641.48
   579.3 2646.35   609.3 2663.91   619.3 2668.58   659.3 2681.78   669.2  2682.1
   689.2 2687.26   709.2 2688.05   749.2 2682.91   789.2 2679.58   819.1 2675.12
#Mann= 3 , 0 , 0
       0      .1       0   409.5    .045       0   422.2      .1       0
Bank Sta=409.5,422.2
XS Rating Curve= 0 ,0
Exp/Cntr=0.3,0.1

Type RM Length L Ch R = 1 ,10312.3 ,397.5,386.7,375.9
XS GIS Cut Line= 3
     1919340.258      232172.665      1919387.95      232761.509
      1919501.48      232986.822
#Sta/Elev= 30
       0 2686.97    39.4 2676.36    59.1 2674.05    78.8 2669.73   108.3 2665.06
   137.8 2658.38   147.7 2657.97   167.4 2653.92   226.5 2646.25   236.3 2646.29
   305.2 2631.82   324.9 2628.66   344.6 2627.24   403.7 2614.82   433.2 2611.47
   452.9 2607.97   462.8 2607.72   472.6 2609.34   492.3 2613.72   521.8 2616.55
   551.4 2622.24   561.2 2626.95   600.5  2653.6   610.2 2658.99   619.9 2659.35
   639.3 2668.42     649  2670.7   707.2 2679.98   755.7 2680.24   843.1  2677.5
#Mann= 3 , 0 , 0
       0      .1       0   452.9    .045       0   472.6      .1       0
Bank Sta=452.9,472.6
XS Rating Curve= 0 ,0
Exp/Cntr=0.3,0.1

Type RM Length L Ch R = 1 ,9925.6  ,382,369.3,356.6
XS GIS Cut Line= 3
     1918820.643      232423.613     1919055.889      232811.256
     1919285.085      233099.051
#Sta/Elev= 30
       0 2657.51     9.9 2652.63    29.6 2649.24    88.7 2647.77     138 2640.23
   177.4 2640.07   197.2  2637.5   216.9 2641.13   236.6 2652.68   246.4 2656.52
   256.3 2656.48   266.2  2652.9     276 2647.24   295.7 2622.82   325.3 2611.71
   354.9 2603.98   364.7 2602.03   374.6 2601.68   377.7  2601.9   392.7 2603.33
   493.2 2614.05   542.9 2618.17   552.9 2621.82   562.8 2627.34   582.7 2642.38
   612.5 2659.17   622.5  2662.8   632.4 2664.61   751.7 2672.45   821.4 2673.54
#Mann= 3 , 0 , 0
       0      .1       0   377.7    .045       0   392.7      .1       0
Bank Sta=377.7,392.7
XS Rating Curve= 0 ,0
Exp/Cntr=0.3,0.1

Type RM Length L Ch R = 1 ,9556    ,295.3,299.5,303.7
XS GIS Cut Line= 3
     1918393.197      232822.457     1918946.445      233094.814
     1919100.227      233235.821
#Sta/Elev= 30
       0 2650.12    29.8 2653.51    89.5 2657.75   109.4 2659.91   129.3 2660.18
   139.2 2659.04   238.7 2638.07   278.5  2628.4   308.3 2623.77   328.2 2617.42
   358.1 2604.18     378 2599.75   406.7 2596.71   421.7  2595.4   427.7 2595.12
   437.6 2595.51   447.6 2597.28   457.5 2600.04   467.5 2604.46   477.4 2606.93
   507.2 2613.41     547 2620.24   616.6 2655.57   636.5 2666.43   646.5 2669.32
   676.3 2674.09   696.1 2676.36   765.7 2688.77   775.6 2689.72   825.3 2686.33
#Mann= 3 , 0 , 0
       0      .1       0   406.7    .045       0   421.7      .1       0
Bank Sta=406.7,421.7
XS Rating Curve= 0 ,0
Exp/Cntr=0.3,0.1

Type RM Length L Ch R = 1 ,9256.4  ,223.7,217.7,211.8
XS GIS Cut Line= 2
     1918285.804      232975.955     1918930.278      233471.648
#Sta/Elev= 30
       0 2658.16    29.8 2656.18    59.5 2652.66    69.4  2650.5    99.2 2636.84
     119 2631.02   138.8 2622.51   148.7  2616.9   168.6 2608.86   178.5  2606.1
   257.8 2597.75   332.9 2591.31   337.1 2590.97   347.9 2591.55   366.9 2594.16
   426.4 2598.48   446.2 2600.99   535.4 2621.16   545.3 2624.97   555.3 2630.53
   565.2 2637.92   575.1  2642.9   594.9 2650.36   614.8  2660.9   624.7  2664.9
   664.3 2674.84   684.2 2682.35   723.8 2692.95   763.5 2700.75     813 2696.84
#Mann= 3 , 0 , 0
       0      .1       0   332.9    .045       0   347.9      .1       0
Bank Sta=332.9,347.9
XS Rating Curve= 0 ,0
Exp/Cntr=0.3,0.1

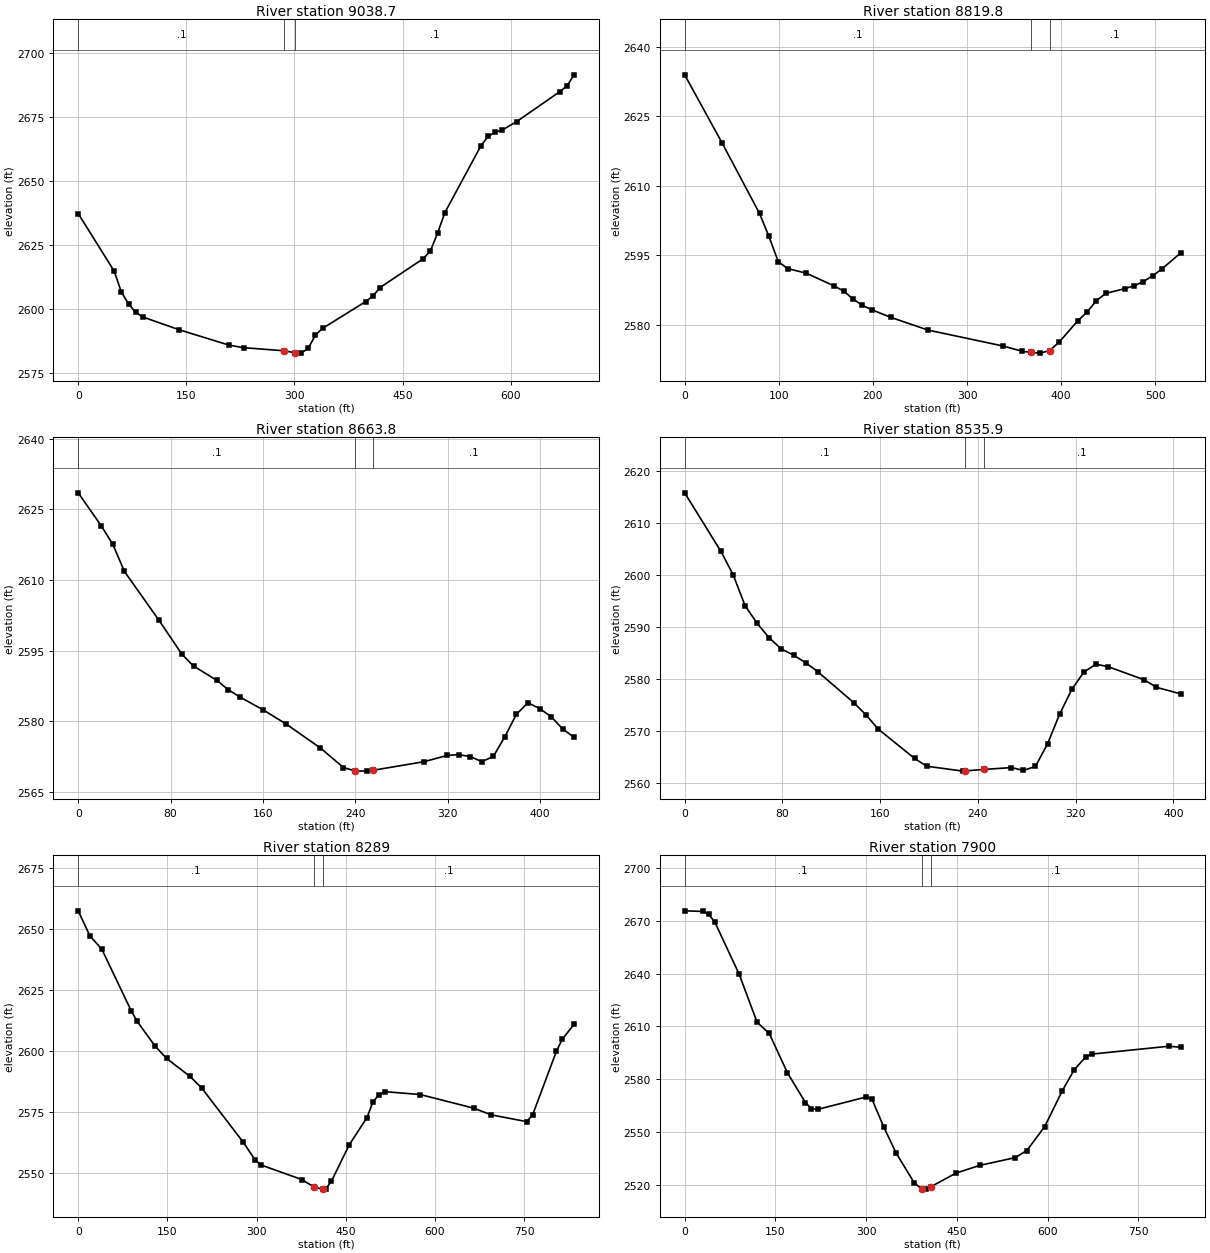
Type RM Length L Ch R = 1 ,9038.7  ,219.2,219,218.9
XS GIS Cut Line= 2
     1918187.803      233263.954     1918823.322      233527.614
#Sta/Elev= 30
       0 2637.22    49.9 2614.71    59.8 2606.54    69.8 2601.94    79.8 2598.52
    89.7 2596.76   139.6  2591.8   209.4 2585.73   229.4 2584.75   286.1 2583.53
   301.1 2582.72   309.1 2582.62   319.1 2584.48   329.1 2589.72     339  2592.3
   398.9 2602.81   408.8 2604.96   418.8 2608.29   478.6 2619.56   488.6  2622.6
   498.6 2629.61   508.6 2637.58   558.4  2663.6   568.4 2667.38   578.4 2669.06
   588.3 2669.91   608.3 2673.22   668.1 2684.91   678.1 2687.21     688  2691.5
#Mann= 3 , 0 , 0
       0      .1       0   286.1    .045       0   301.1      .1       0
Bank Sta=286.1,301.1
XS Rating Curve= 0 ,0
Exp/Cntr=0.3,0.1

Type RM Length L Ch R = 1 ,8819.8  ,152.5,155.8,159.2
XS GIS Cut Line= 2
     1918083.334      233460.455     1918572.099      233656.956
#Sta/Elev= 30
       0    2634    39.8 2619.25    79.5 2604.02    89.4  2599.1    99.4 2593.61
   109.3  2592.1   129.2  2591.1     159 2588.32     169 2587.21   178.9 2585.52
   188.8 2584.13   198.8 2583.19   218.7 2581.56   258.4  2578.8   337.9 2575.36
   357.8 2574.26   367.8 2573.95   377.7 2573.81   387.6 2574.37   397.6 2576.14
   417.4 2580.78   427.4 2582.68   437.3 2585.14   447.3 2586.74   467.2 2587.74
   477.1 2588.35     487 2589.26     497 2590.52   506.9 2592.02   526.8 2595.46
#Mann= 3 , 0 , 0
       0      .1       0   367.8    .045       0   387.6      .1       0
Bank Sta=367.8,387.6
XS Rating Curve= 0 ,0
Exp/Cntr=0.3,0.1

Type RM Length L Ch R = 1 ,8663.8  ,119.7,127.8,136.6
XS GIS Cut Line= 2
     1918058.544      233551.602     1918429.151      233769.056
#Sta/Elev= 30
       0  2628.5      20 2621.48      30 2617.56      40 2611.83      70 2601.44
    89.9 2594.22    99.9 2591.74   119.9 2588.72   129.9 2586.74   139.9 2585.18
   159.9 2582.48   179.9 2579.47   209.8 2574.35   229.8 2570.19     240 2569.47
   249.8 2569.43     255 2569.59   299.8 2571.44   319.8 2572.77   329.8 2572.93
   339.8  2572.5   349.8 2571.44   359.7 2572.55   369.7 2576.76   379.7 2581.51
   389.7 2583.94   399.7 2582.72   409.7 2581.01   419.7 2578.39   429.7 2576.59
#Mann= 3 , 0 , 0
       0      .1       0     240    .045       0     255      .1       0
Bank Sta=240,255
XS Rating Curve= 0 ,0
Exp/Cntr=0.3,0.1

Type RM Length L Ch R = 1 ,8535.9  ,253.4,246.9,238.8
XS GIS Cut Line= 2
     1918055.974      233635.813     1918356.943      233908.179
#Sta/Elev= 30
       0  2615.8    29.7 2604.52    39.6 2600.08    49.5 2594.07    59.4 2590.68
    69.3 2587.88    79.2 2585.76    89.1 2584.59      99 2583.14   108.9 2581.42
   138.6 2575.41   148.5 2573.07   158.4 2570.37   188.1 2564.74     198 2563.24
   227.7 2562.29   229.7 2562.34   244.7 2562.61   267.3 2562.97   277.2 2562.43
   287.1 2563.19     297 2567.55   306.9 2573.26   316.8 2577.99   326.7 2581.33
   336.6 2582.85   346.5 2582.38   376.2 2579.84   386.1  2578.4   405.9 2577.15
#Mann= 3 , 0 , 0
       0      .1       0   229.7    .045       0   244.7      .1       0
Bank Sta=229.7,244.7
XS Rating Curve= 0 ,0
Exp/Cntr=0.3,0.1

Type RM Length L Ch R = 1 ,8289    ,385.9,388.9,393.6
XS GIS Cut Line= 3
     1917765.808      233766.399     1918112.504      233996.493
     1918478.229      234199.501
#Sta/Elev= 30
       0 2657.52    19.8 2647.18    39.6 2641.83    89.2 2616.47    99.1 2612.18
   128.8 2602.18   148.6 2596.95   188.2 2589.54     208 2584.74   277.4 2562.64
   297.2 2555.44   307.1 2553.26   376.5 2547.21   396.4 2544.21   411.4 2543.32
   416.1 2543.31   426.1 2546.58   455.9 2561.45   485.8 2572.66   495.8 2579.02
   505.7 2582.04   515.7 2583.32   575.4 2582.13   665.1 2576.56     695 2573.79
   754.7    2571   764.7 2573.89   804.5 2599.86   814.5 2604.85   834.4 2610.99
#Mann= 3 , 0 , 0
       0      .1       0   396.4    .045       0   411.4      .1       0
Bank Sta=396.4,411.4
XS Rating Curve= 0 ,0
Exp/Cntr=0.3,0.1

Type RM Length L Ch R = 1 ,7900    ,391.1,398.4,404.4
XS GIS Cut Line= 3
     1917519.591      233978.695     1917827.631      234248.216
     1918116.644      234539.887
#Sta/Elev= 30
       0 2675.81      30 2675.47    39.9  2673.8    49.9 2669.33    89.8 2639.96
   119.8 2612.34   139.8 2606.06   169.7 2583.74   199.7 2566.65   209.6 2563.28
   219.6  2562.8   299.5 2569.82   309.5 2568.76   329.4 2552.59   349.4 2538.09
   379.4  2521.1   391.9 2517.47   399.3 2517.44   406.9 2518.79   448.4 2526.54
   487.5 2530.92   546.2 2535.35   565.7 2539.42   595.1 2552.98   624.4 2573.46
   643.9 2585.29   663.5 2592.89   673.3 2594.28   800.4 2598.76   819.9 2598.18
#Mann= 3 , 0 , 0
       0      .1       0   391.9    .045       0   406.9      .1       0
Bank Sta=391.9,406.9
XS Rating Curve= 0 ,0
Exp/Cntr=0.3,0.1

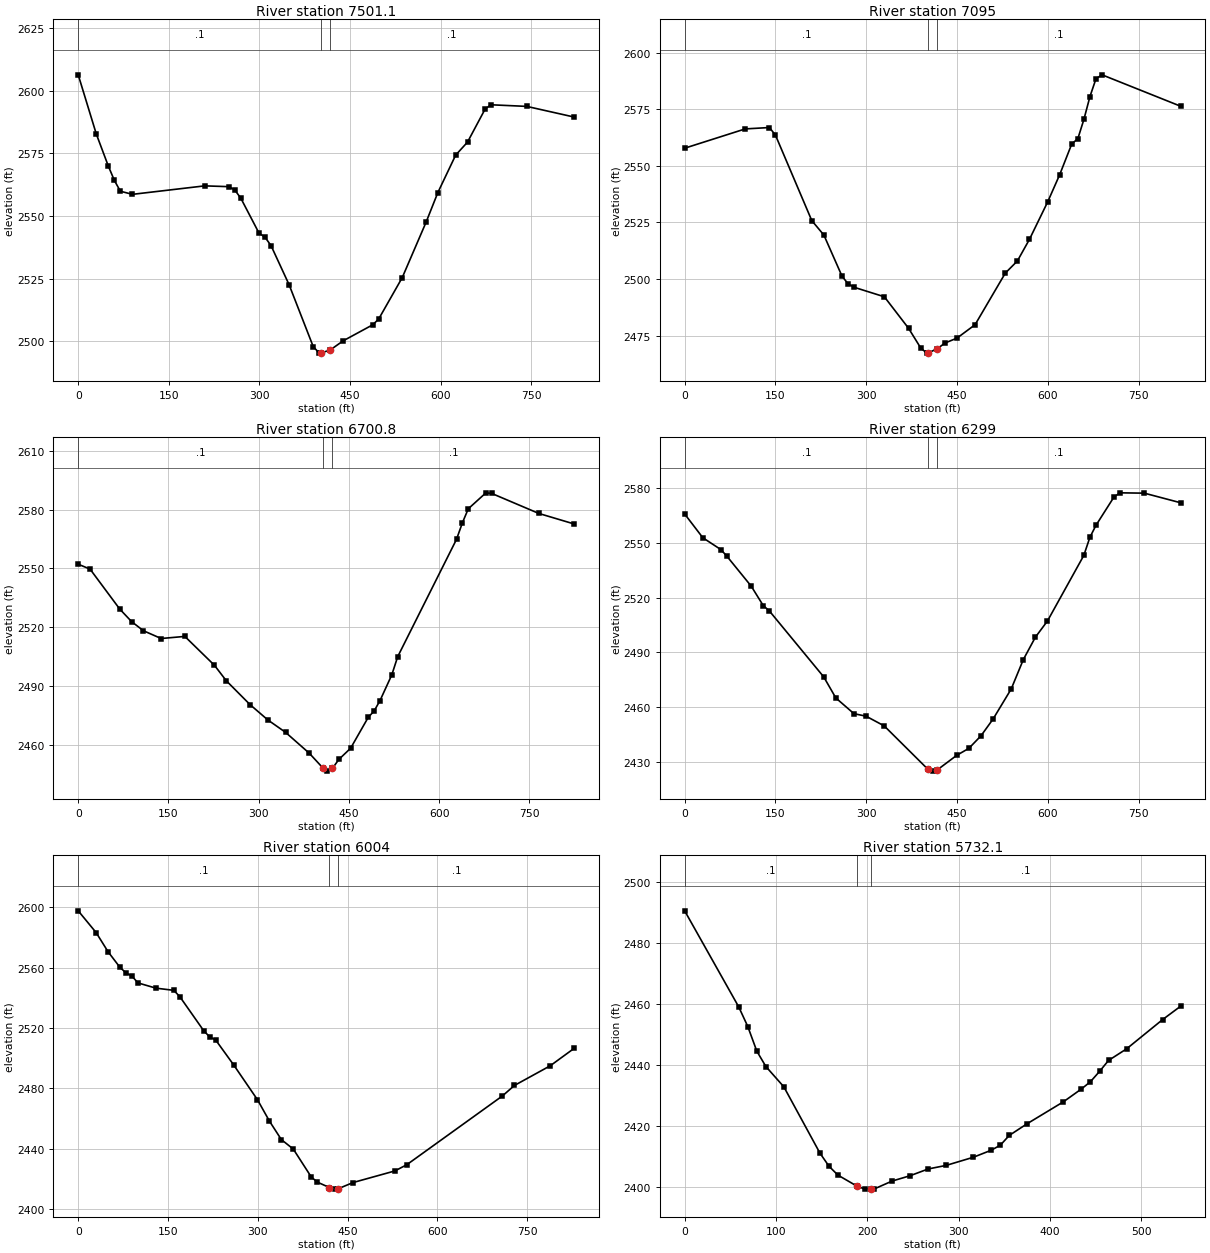
Type RM Length L Ch R = 1 ,7501.1  ,405.7,406.1,407.2
XS GIS Cut Line= 3
     1917338.208        234168.6     1917543.694      234522.321
     1917756.045      234875.573
#Sta/Elev= 30
       0 2606.26    29.9 2582.71    49.9 2569.87    59.9 2564.16    69.8 2559.87
    89.8 2558.63   209.5 2562.01   249.4 2561.69   259.4 2560.34   269.4 2557.02
   299.3 2543.21   309.3 2541.55   319.3 2538.18   349.2 2522.61   389.1 2497.97
   399.1 2495.35   401.6 2495.46   416.6 2496.48   438.5 2500.22   487.6 2506.63
   497.4 2508.89   536.6 2525.48   575.9 2547.46   595.5 2559.34     625 2574.26
   644.6 2579.44     674 2592.72   683.8 2594.32   742.7 2593.68   821.2 2589.43
#Mann= 3 , 0 , 0
       0      .1       0   401.6    .045       0   416.6      .1       0
Bank Sta=401.6,416.6
XS Rating Curve= 0 ,0
Exp/Cntr=0.3,0.1

Type RM Length L Ch R = 1 ,7095    ,404.2,393.9,383.6
XS GIS Cut Line= 3
     1917041.156      234422.174     1917243.599      234778.597
     1917437.182      235139.446
#Sta/Elev= 30
       0 2557.81     100 2566.33     140 2566.94     150 2563.57     210 2525.82
     230 2519.42   259.9 2501.29   269.9 2497.88   279.9 2496.35   329.9 2492.15
   369.9 2478.23   389.9 2469.57   399.9 2467.25   402.4 2467.37   417.4 2469.18
   429.9  2471.7   449.8 2473.86   479.8 2479.81   529.8 2502.63   549.7 2507.98
   569.7 2517.56   599.7 2534.05   619.6  2546.1   639.6 2559.72   649.6 2562.01
   659.6 2570.53   669.6 2580.63   679.6 2588.53   689.6 2590.23   819.4 2576.36
#Mann= 3 , 0 , 0
       0      .1       0   402.4    .045       0   417.4      .1       0
Bank Sta=402.4,417.4
XS Rating Curve= 0 ,0
Exp/Cntr=0.3,0.1

Type RM Length L Ch R = 1 ,6700.8  ,400.3,401.9,403.5
XS GIS Cut Line= 3
     1916604.725       234799.16     1916946.636      235032.241
      1917279.41      235273.128
#Sta/Elev= 30
       0 2552.18    19.7 2549.68      69  2529.3    88.7  2522.9   108.4 2518.22
   137.9 2514.25   177.3 2515.32   226.6 2500.55   246.3 2492.66   285.7  2480.5
   315.3 2472.68   344.8 2466.34   384.2 2455.69   407.6 2447.91   413.8 2446.55
   422.6 2447.91   433.4 2452.54   452.9 2458.22   482.3 2474.05     492 2477.25
   501.8 2482.56   521.4  2495.7   531.2 2504.97     629 2564.88   638.8 2573.34
   648.6 2580.49   677.9 2588.62   687.7 2588.29   765.9 2578.09   824.6 2572.72
#Mann= 3 , 0 , 0
       0      .1       0   407.6    .045       0   422.6      .1       0
Bank Sta=407.6,422.6
XS Rating Curve= 0 ,0
Exp/Cntr=0.3,0.1

Type RM Length L Ch R = 1 ,6299    ,289.3,294.4,298.9
XS GIS Cut Line= 3
     1916370.717      235083.619     1916691.376      235338.251
     1917004.623      235602.337
#Sta/Elev= 30
       0  2565.7      30 2552.71    59.9 2546.22    69.9 2542.54   109.9 2526.24
   129.8 2515.61   139.8 2512.72   229.7  2476.6   249.7 2465.09   279.6  2456.5
   299.6 2455.13   329.6 2449.81     402 2426.02   409.5 2425.08     417 2425.69
   449.4 2433.73   469.4 2437.53   489.4 2444.38   509.4 2453.56   539.4 2470.03
   559.4  2486.1   579.3 2498.32   599.3 2507.22   659.3 2543.05   669.3 2552.92
   679.3 2559.47   709.2 2575.04   719.2 2577.28   759.2  2577.1   819.2 2571.85
#Mann= 3 , 0 , 0
       0      .1       0     402    .045       0     417      .1       0
Bank Sta=402,417
XS Rating Curve= 0 ,0
Exp/Cntr=0.3,0.1

Type RM Length L Ch R = 1 ,6004    ,280.7,272.1,263.4
XS GIS Cut Line= 2
       1916202.3       235181.03     1916717.979       235829.33
#Sta/Elev= 30
       0  2597.6    29.9 2583.21    49.9 2570.49    69.9 2560.09    79.8 2556.54
    89.8 2554.37    99.8 2549.88   129.8 2546.41   159.7 2544.96   169.7 2540.78
   209.6 2518.25   219.6 2514.15   229.6  2512.1   259.5 2495.69   299.4 2472.56
   319.4  2458.4   339.3 2446.16   359.3 2439.86   389.2 2421.46   399.2 2418.04
   419.7  2414.4   429.2 2413.36   434.7 2413.69   459.1 2417.72     529 2425.41
   548.9 2429.53   708.6 2475.06   728.6 2481.98   788.5 2495.03   828.4 2506.56
#Mann= 3 , 0 , 0
       0      .1       0   419.7    .045       0   434.7      .1       0
Bank Sta=419.7,434.7
XS Rating Curve= 0 ,0
Exp/Cntr=0.3,0.1

Type RM Length L Ch R = 1 ,5732.1  ,246.3,243.2,241.3
XS GIS Cut Line= 2
     1916094.697      235585.897     1916562.319      235861.993
#Sta/Elev= 30
       0 2490.54    59.2 2458.98    69.1 2452.55      79 2444.45    88.9 2439.42
   108.6 2432.74   148.1 2410.98     158 2406.68   167.8 2403.76   188.8 2400.11
   197.5 2399.16   203.8 2399.19   207.4  2399.2   227.1 2401.81   246.8 2403.56
   266.6 2405.78   286.3 2406.95     316 2409.62   335.7 2411.94   345.6 2413.59
   355.4  2416.8   375.2 2420.68   414.7 2427.84   434.4 2432.05   444.3 2434.44
   454.2  2437.8   464.1 2441.42   483.8 2445.21   523.3 2454.83     543 2459.22
#Mann= 3 , 0 , 0
       0      .1       0   188.8    .045       0   203.8      .1       0
Bank Sta=188.8,203.8
XS Rating Curve= 0 ,0
Exp/Cntr=0.3,0.1

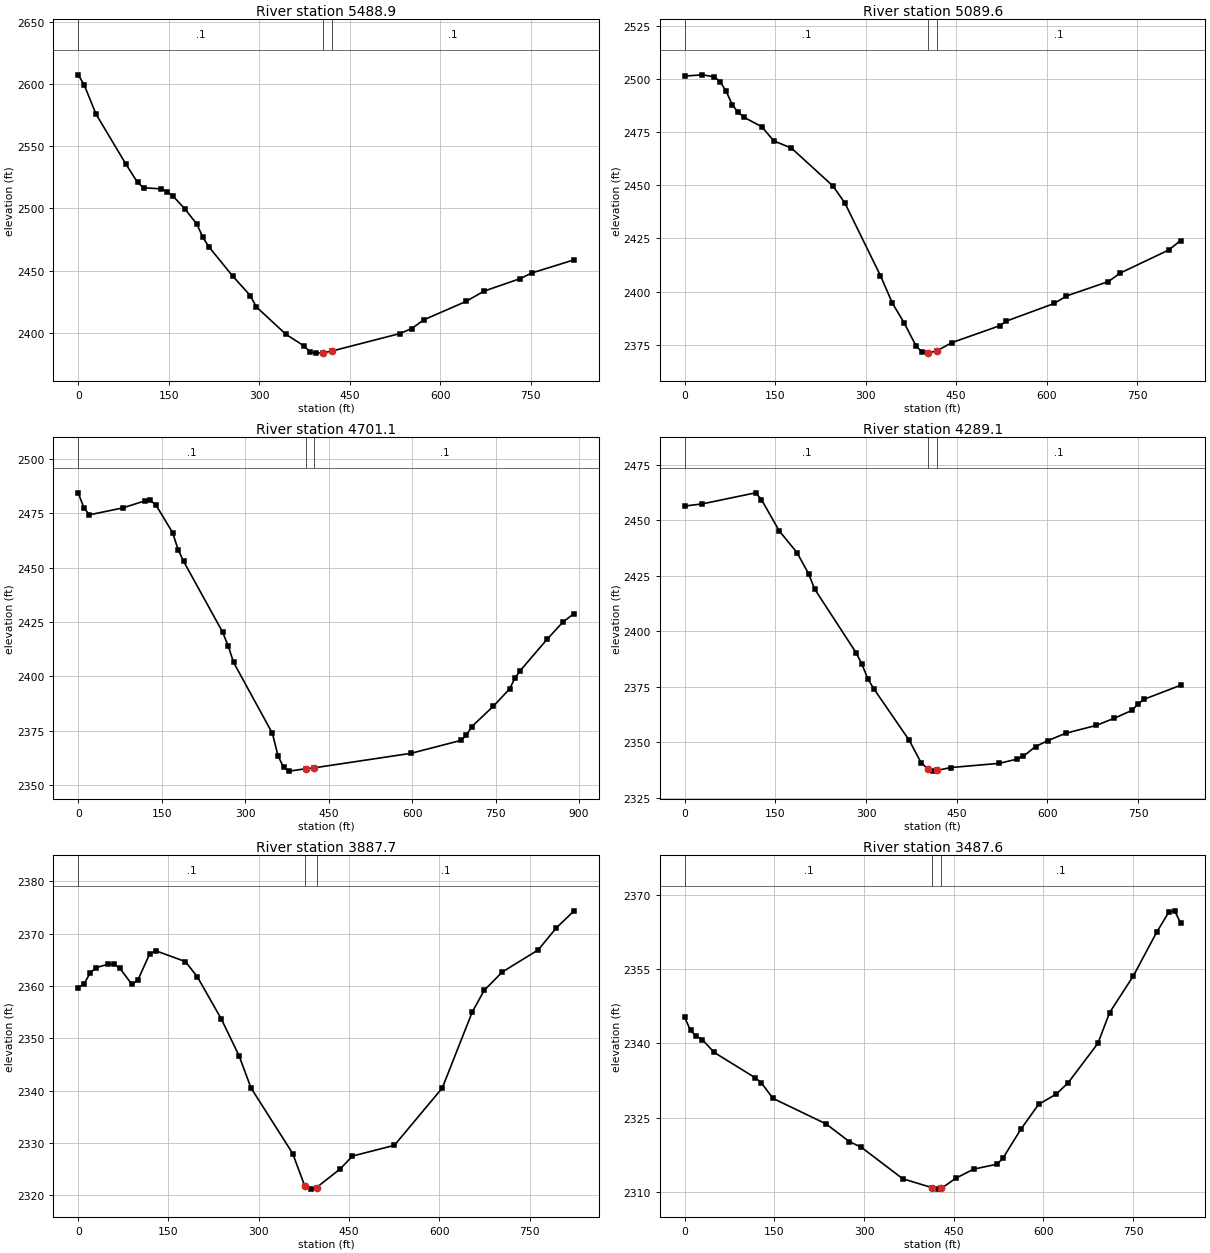
Type RM Length L Ch R = 1 ,5488.9  ,398.5,399.3,400
XS GIS Cut Line= 3
     1915808.345       235754.34     1916189.122      235915.252
     1916556.747      236094.087
#Sta/Elev= 30
       0 2607.25     9.8 2599.31    29.5  2575.7    78.7  2535.8    98.4 2520.76
   108.3 2516.53   137.8 2515.61   147.6 2513.38   157.5 2509.63   177.2 2499.33
   196.8 2487.19   206.7 2476.67   216.5 2469.12   255.9 2445.67   285.4 2429.82
   295.3 2420.81   344.5 2398.72     374 2389.57   383.8 2384.91   393.7 2383.66
   405.9 2383.95   420.9 2385.38     533 2399.35     553 2403.44   572.9 2410.41
   642.7 2425.14   672.6 2433.42   732.5  2443.5   752.4 2448.12   822.2 2458.63
#Mann= 3 , 0 , 0
       0      .1       0   405.9    .045       0   420.9      .1       0
Bank Sta=405.9,420.9
XS Rating Curve= 0 ,0
Exp/Cntr=0.3,0.1

Type RM Length L Ch R = 1 ,5089.6  ,391.5,388.4,384.1
XS GIS Cut Line= 3
      1915690.43      236118.209     1916065.406       236291.32
     1916425.984      236484.053
#Sta/Elev= 30
       0 2501.32    29.5  2501.9    49.2 2500.95      59 2498.59    68.8 2494.14
    78.7 2487.91    88.5 2484.27    98.3 2481.94   127.8  2477.5   147.5 2470.89
     177 2467.44   245.8 2449.63   265.5 2441.63   324.5 2407.48   344.2  2394.6
   363.8 2385.28   383.5 2374.42   393.3 2371.63   403.2 2371.09   403.6 2371.11
   418.6 2372.25   442.9 2376.04   522.7 2384.02   532.7  2386.1   612.4 2394.43
   632.4 2397.93   702.2 2404.72   722.1 2408.77   801.9 2419.51   821.9    2424
#Mann= 3 , 0 , 0
       0      .1       0   403.6    .045       0   418.6      .1       0
Bank Sta=403.6,418.6
XS Rating Curve= 0 ,0
Exp/Cntr=0.3,0.1

Type RM Length L Ch R = 1 ,4701.1  ,409.7,412,415.1
XS GIS Cut Line= 3
     1915506.703      236515.716     1916155.637      236712.668
     1916362.087      236764.902
#Sta/Elev= 30
       0 2484.33      10 2477.57      20 2474.23    79.8 2477.38   119.7 2480.64
   129.6 2480.81   139.6 2478.76   169.5 2466.09   179.5 2458.27   189.5  2452.8
   259.3 2420.44   269.3 2414.12   279.2 2406.43     349 2373.82     359 2363.55
     369 2358.18     379 2356.51   409.4 2357.63   424.4 2358.04   598.4 2364.71
   687.8 2370.64   697.5 2373.06   707.2 2376.97   745.9 2386.32     775 2394.23
   784.6 2399.16   794.3 2402.69   842.7 2417.15   871.8  2425.2   891.1 2428.87
#Mann= 3 , 0 , 0
       0      .1       0   409.4    .045       0   424.4      .1       0
Bank Sta=409.4,424.4
XS Rating Curve= 0 ,0
Exp/Cntr=0.3,0.1

Type RM Length L Ch R = 1 ,4289.1  ,403.3,401.3,395.1
XS GIS Cut Line= 3
     1915414.649      236858.181     1915791.386      237021.076
     1916162.096      237195.909
#Sta/Elev= 30
       0 2456.33    29.3 2457.31   117.3 2462.28     127 2459.25   156.4 2445.15
   185.7 2435.43   205.2 2425.75     215 2418.96   283.4 2390.39   293.2 2385.19
     303 2378.56   312.7 2374.17   371.4 2350.94   390.9 2340.91   402.9 2337.87
   410.4 2337.07   417.9 2337.44   440.4 2338.68   520.4 2340.58   550.4 2342.51
   560.4  2343.8   580.4 2348.14   600.4 2350.75   630.4 2354.12   680.4 2357.62
   710.4 2360.84   740.3 2364.47   750.3 2367.46   760.3 2369.44   820.3  2375.7
#Mann= 3 , 0 , 0
       0      .1       0   402.9    .045       0   417.9      .1       0
Bank Sta=402.9,417.9
XS Rating Curve= 0 ,0
Exp/Cntr=0.3,0.1

Type RM Length L Ch R = 1 ,3887.7  ,379.9,399.6,422.9
XS GIS Cut Line= 3
      1915268.93      237264.792     1915663.074      237397.065
     1916066.093      237463.126
#Sta/Elev= 30
       0 2359.69     9.9 2360.41    19.8 2362.51    29.7  2363.5    49.5 2364.17
    59.4 2364.17    69.3 2363.38    89.1 2360.31      99  2361.1   118.8 2366.15
   128.7 2366.74   178.2 2364.66     198 2361.74   237.6 2353.73   267.3 2346.65
   287.1 2340.51   356.4 2327.97   376.2 2321.84     386 2321.16     396 2321.47
   435.7 2325.05   455.6 2327.48   525.3 2329.53     605  2340.5   654.8 2355.04
   674.7 2359.17   704.6 2362.67   764.4  2366.9   794.3 2371.09   824.1 2374.37
#Mann= 3 , 0 , 0
       0      .1       0   376.2    .045       0     396      .1       0
Bank Sta=376.2,396
XS Rating Curve= 0 ,0
Exp/Cntr=0.3,0.1

Type RM Length L Ch R = 1 ,3487.6  ,248.1,249.1,250.1
XS GIS Cut Line= 3
     1915202.374      237354.619     1915373.365      237570.804
     1915597.295      238077.276
#Sta/Elev= 30
       0 2345.21     9.8 2342.59    19.7 2341.42    29.5 2340.73    49.2 2338.16
   118.1 2333.02     128 2332.04   147.7 2328.86   236.3 2323.72   275.6 2320.11
   295.4 2318.99   364.6 2312.63   414.3  2310.8     424 2310.53   429.3 2310.69
   453.6 2312.74   483.3 2314.57   522.8 2315.58   532.7 2316.87   562.4 2322.66
   592.1 2327.68   621.7 2329.74   641.5 2332.05     691 2339.97   710.7 2346.21
   750.3  2353.6   789.8 2362.53   809.6 2366.48   819.5 2366.76   829.4 2364.28
#Mann= 3 , 0 , 0
       0      .1       0   414.3    .045       0   429.3      .1       0
Bank Sta=414.3,429.3
XS Rating Curve= 0 ,0
Exp/Cntr=0.3,0.1

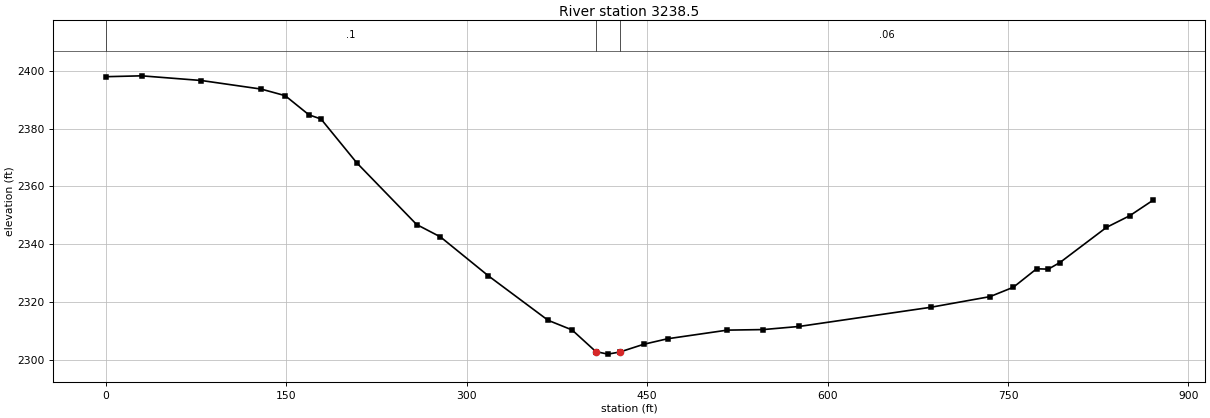
Type RM Length L Ch R = 1 ,3238.5  ,3260.6,3237.4,3213.1
XS GIS Cut Line= 3
     1915056.227      237416.588      1915321.13      238091.904
     1915401.969      238212.541
#Sta/Elev= 30
       0 2397.97    29.8 2398.27    79.5 2396.65   129.2 2393.68   149.1 2391.41
   168.9 2384.76   178.9 2383.33   208.7 2368.13   258.4  2346.8   278.2 2342.51
     318 2329.05   367.7 2313.64   387.6 2310.31   407.4  2302.8   417.4 2301.93
   427.3 2302.66   447.2 2305.34     467 2307.25   516.7 2310.24   546.5 2310.43
   576.4 2311.51   685.7 2318.14   735.1 2321.84   754.5 2325.09   773.8 2331.47
   783.5 2331.35   793.2 2333.64   831.9 2345.81   851.3 2349.86   870.6 2355.21
#Mann= 3 , 0 , 0
       0      .1       0   407.4    .045       0   427.3     .06       0
Bank Sta=407.4,427.3
XS Rating Curve= 0 ,0
Exp/Cntr=0.3,0.1

Chan Stop Cuts=-1
Use User Specified Reach Order=0
Composite Channel Slope=5